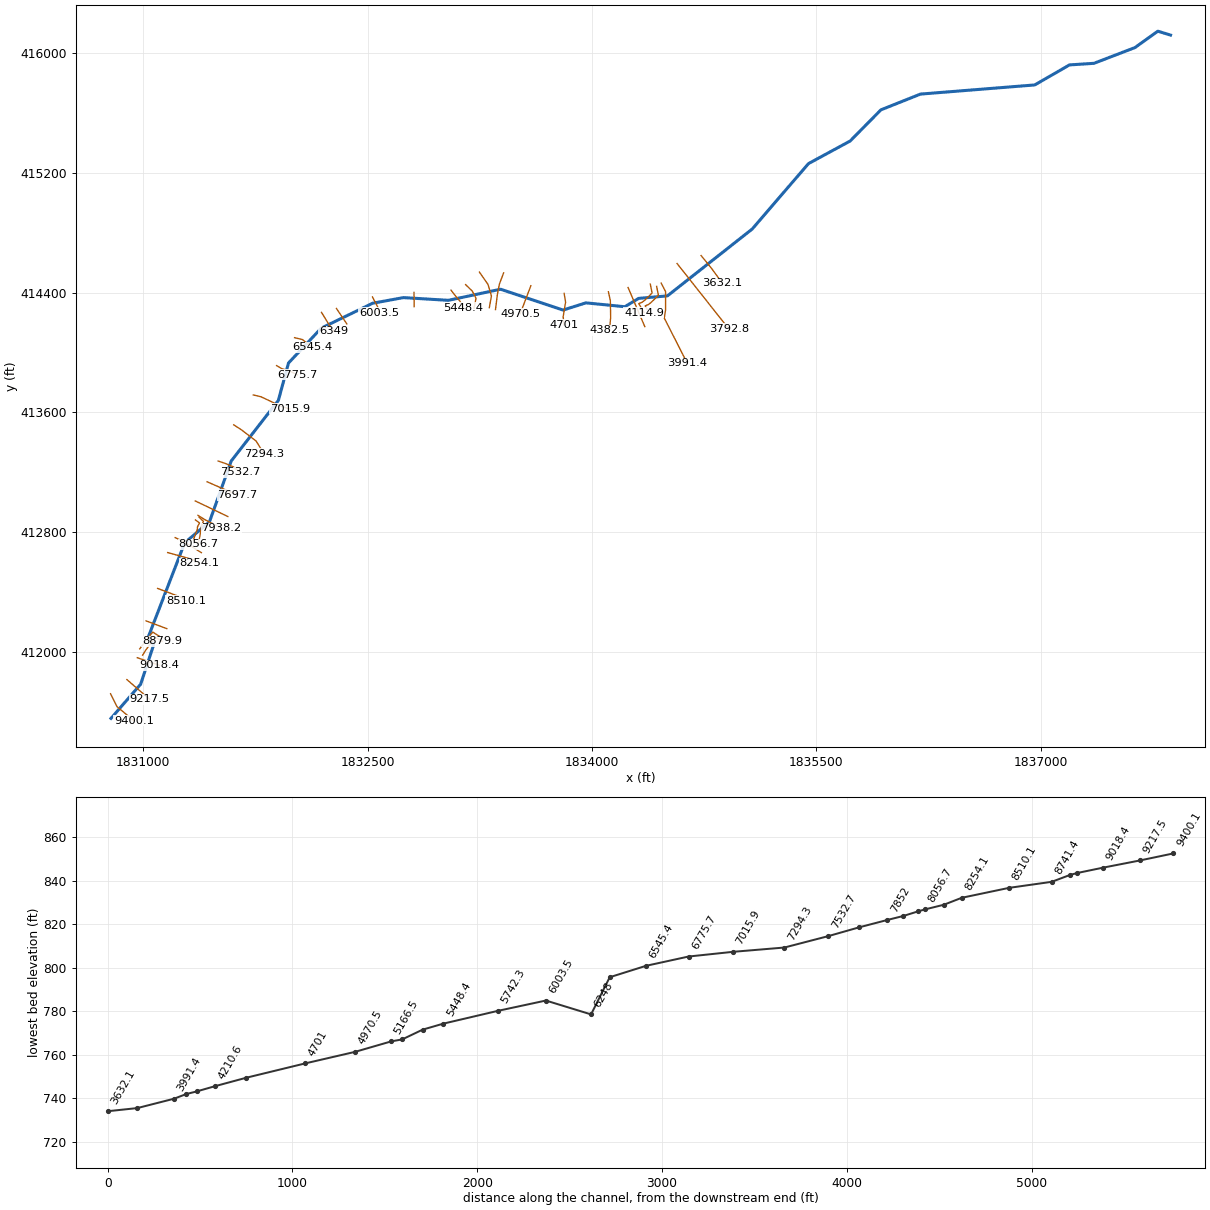
--- LNGBTTMCK.prj (project) ---

Proj Title=LNGBTTMCK
Current Plan=p01
Default Exp/Contr=0,0
English Units
Geom File=g01
Flow File=f01
Plan File=p01
BEGIN DESCRIPTION:
END DESCRIPTION:
DSS Export Rating Curves= 0
DSS Export Rating Curve Sorted= 0
DSS Export Volume Flow Curves= 0
DXF OffsetX= 0
DXF OffsetY= 0
DXF ScaleX= 0
DXF ScaleY= 0

--- LNGBTTMCK.p01 (plan) ---

Plan Title=Floodplain
Program Version=4.00
Geom File=g01
Flow File=f01
K Sum by GR=0
Std Step Tol=0.01
Critical Tol=0.01
Num of Std Step Trials=20
Max Error Tol=0.3
Flow Tol Ratio=0.001
Split Flow NTrial=30
Split Flow Tol=0.02
Split Flow Ratio=0.02
Log Output Level=0
Friction Slope Method=1
Unsteady Friction Slope Method=2
Unsteady Bridges Friction Slope Method=1
Global Log Level=0
CheckData=False
Run HTab=0
Run UNet=0
Run PostProcess=0
UNET Theta=0
UNET Theta Warmup=0
UNET ZTol=0
UNET ZSATol=0
UNET MxIter=0
UNET MaxInSteps=0
UNET DtIC=0
UNET DtMin=0
UNET MaxCRTS=0
UNET WFStab=0
UNET SFStab=0
UNET WFX=0
UNET SFX=0
UNET DSS MLevel=0
UNET DZMax Abort=0
UNET Convert EG Bridges=0
UNET Use Existing IB Tables=0
UNET Froude Limit=0
UNET Froude Power=0
Write IC File=0
Echo Input=False
Echo Output=False
Write Detailed=0

--- LNGBTTMCK.f01 (steady flow) ---

Flow Title=NFF Regression Equation
Program Version=4.10
Number of Profiles= 1
Profile Names=P100yr
River Rch & RM=LNGBTTMCK,Main            ,9400.1
723.9512
River Rch & RM=LNGBTTMCK,Main            ,9018.4
1074.948
River Rch & RM=LNGBTTMCK,Main            ,6349
 1184.85
River Rch & RM=LNGBTTMCK,Main            ,3632.1
1921.501
River Rch & RM=LNGBTTMCK,Main            ,595.1
2000.702
Boundary for River Rch & Prof#=LNGBTTMCK,Main            , 1
Up Type= 0
Dn Type= 3
Dn Slope=0.01
DSS Import GetInterval= 0
DSS Import GetPeak= 0
DSS Import FillOption= 0

--- LNGBTTMCK.g01 (geometry) ---

Geom Title=USGS 10m DEM
Program Version=4.10

River Reach=LNGBTTMCK       ,Main
Reach XY= 30
     1830783.918      411553.134     1830982.269      411781.867
     1831068.206      412042.284     1831036.219      412105.435
      1831276.54      412727.179     1831441.904      412866.502
     1831587.738      413274.054     1831902.842      413679.002
      1831970.55      413929.002       1832189.3      414162.075
      1832533.05      414328.742     1832738.779      414366.502
     1833039.561      414348.273     1833388.519      414422.492
     1833806.488      414283.169     1833958.831      414331.346
     1834219.406      414305.488     1834311.696      414361.294
     1834504.404      414378.221     1835070.811      414824.836
     1835447.113      415262.336     1835725.759      415413.377
     1835931.488      415621.711     1836195.811      415727.179
     1836960.134      415788.377     1837192.225      415922.255
     1837355.967      415932.909     1837630.706      416038.377
      1837783.05      416147.752      1837868.03      416121.636

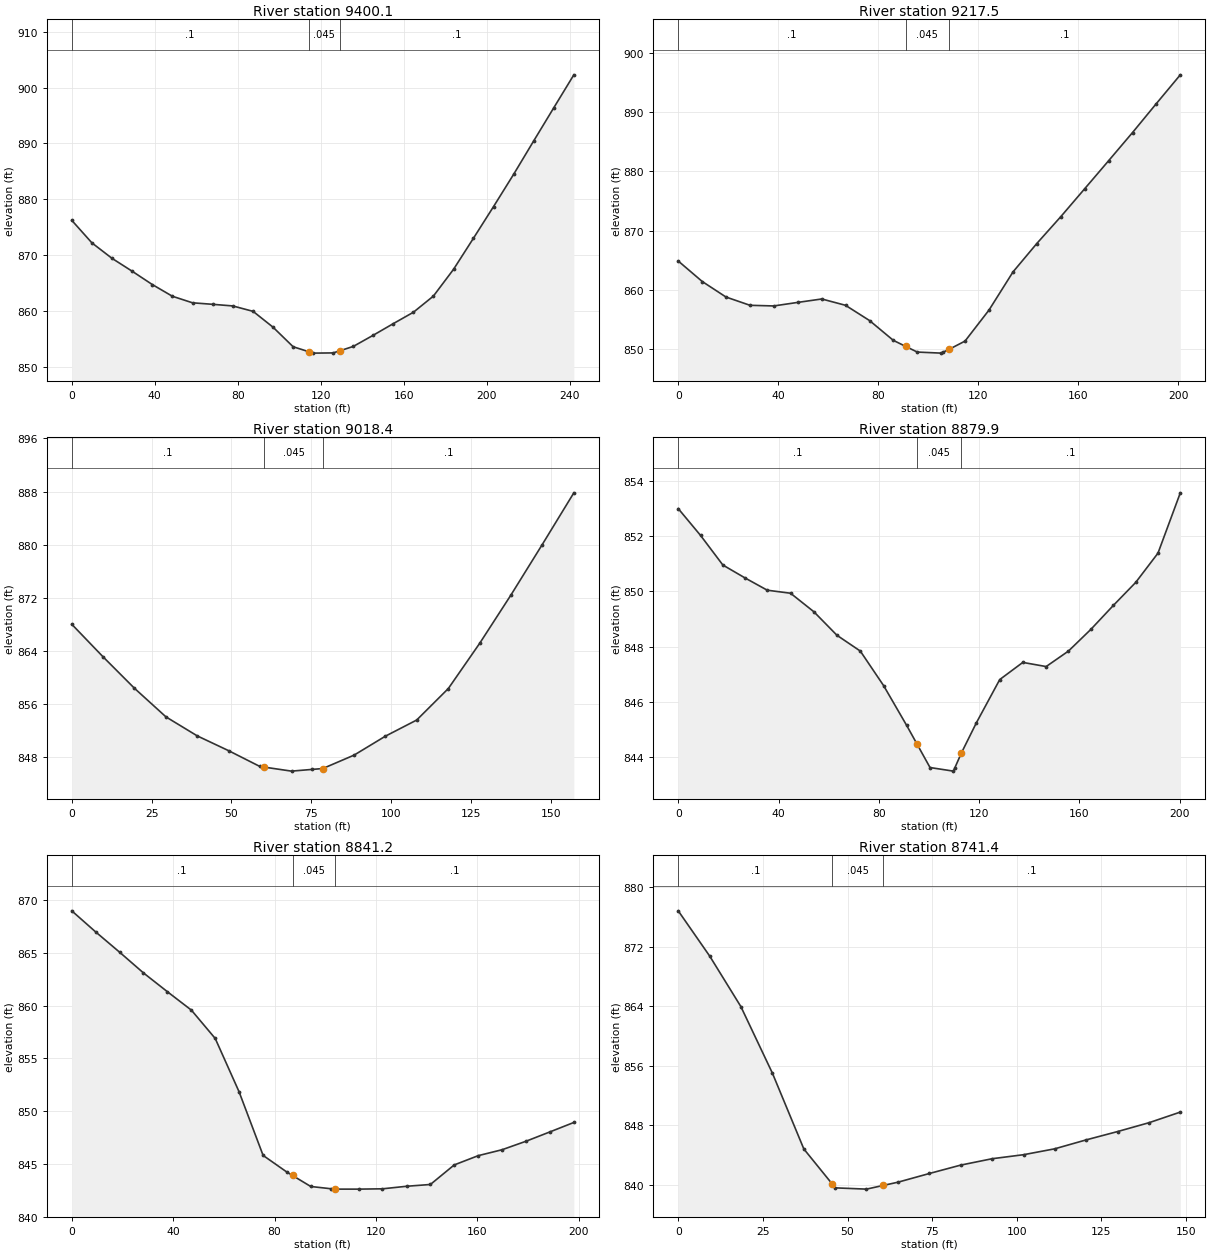
Type RM Length L Ch R = 1 ,9400.1  ,183,182.5,181.8
XS GIS Cut Line= 3
     1830780.793       411717.92     1830824.196      411631.115
     1830935.958      411538.884
#Sta/Elev= 28
       0  876.25     9.7  872.22    19.4  869.45    29.1  867.15    38.8  864.77
    48.5  862.67    58.2   861.5    67.9  861.23    77.6  860.94    87.4  859.97
      97  857.14   106.7  853.64   114.2  852.76   116.4   852.5     126  852.54
   129.2  852.92   135.7   853.7   145.4  855.72     155  857.78   164.7  859.82
   174.3   862.7     184  867.48   193.6  873.04   203.3  878.71     213  884.49
   222.6  890.42   232.3  896.36     242  902.27
#Mann= 3 , 0 , 0
       0      .1       0   114.2    .045       0   129.2      .1       0
Bank Sta=114.2,129.2
XS Rating Curve= 0 ,0
Exp/Cntr=0.3,0.1

Type RM Length L Ch R = 1 ,9217.5  ,190.4,199.1,207.8
XS GIS Cut Line= 2
     1830890.385      411812.321     1831042.295      411681.028
#Sta/Elev= 25
       0  864.84     9.6  861.37    19.1  858.74    28.7  857.34    38.2  857.23
    47.8  857.83    57.4  858.41    66.9  857.34    76.5  854.76      86  851.41
    90.9  850.39    95.6  849.42   105.2  849.24   105.9  849.39  108.28  849.87
   114.7  851.28   124.3  856.54   133.9     863   143.4   867.8     153  872.35
   162.5  877.05   172.1  881.81   181.7   886.6   191.2  891.49   200.8  896.37
#Mann= 3 , 0 , 0
       0      .1       0    90.9    .045       0  108.28      .1       0
Bank Sta=90.9,108.28
XS Rating Curve= 0 ,0
Exp/Cntr=0.3,0.1

Type RM Length L Ch R = 1 ,9018.4  ,107.3,138.4,169.1
XS GIS Cut Line= 2
      1830959.83      411958.806     1831108.484      411907.807
#Sta/Elev= 19
       0  868.04     9.8  863.14    19.6  858.42    29.5   854.1    39.3  851.24
    49.1  849.02    58.9  846.64    60.3  846.54    68.8  845.94    75.3   846.2
    78.6  846.33    88.4  848.35    98.2   851.2     108  853.63   117.9  858.37
   127.7  865.16   137.5  872.44   147.3  880.03   157.2  887.82
#Mann= 3 , 0 , 0
       0      .1       0    60.3    .045       0    78.6      .1       0
Bank Sta=60.3,78.6
XS Rating Curve= 0 ,0
Exp/Cntr=0.3,0.1

Type RM Length L Ch R = 1 ,8879.9  ,36.9,38.8,51.6
XS GIS Cut Line= 4
     1830995.637      411976.167     1831014.083      412006.549
     1831079.099      412096.732     1831124.738      412068.747
#Sta/Elev= 26
       0  852.99     8.9  852.02    17.8  850.95    26.7  850.48    35.5  850.04
    44.8  849.93    54.1  849.26    63.3  848.41    72.6  847.84    81.9  846.59
    91.1  845.15    95.2  844.48   100.4  843.63   109.7   843.5   110.2   843.6
  112.93  844.16   118.9  845.25   128.2  846.81   137.4  847.43   146.7  847.28
   155.6  847.84   164.6  848.63   173.5  849.49   182.4  850.32   191.3  851.38
   200.2  853.56
#Mann= 3 , 0 , 0
       0      .1       0    95.2    .045       0  112.93      .1       0
Bank Sta=95.2,112.93
XS Rating Curve= 0 ,0
Exp/Cntr=0.3,0.1

Type RM Length L Ch R = 1 ,8841.2  ,131.7,99.8,55.9
XS GIS Cut Line= 3
     1830976.106      412018.484     1831062.911      412130.247
     1831110.654      412099.865
#Sta/Elev= 24
       0  868.97     9.4  866.98    18.9  865.05    28.3  863.09    37.7  861.32
  47.201  859.57    56.6  856.89      66  851.85  75.499  845.82  84.901  844.24
    87.1  843.92    94.3  842.88 102.101  842.67 103.799  842.63 113.201  842.63
   122.6  842.66   132.1   842.9 141.499  843.07 150.901  844.92   160.4   845.8
 169.799  846.36 179.201  847.16   188.7  848.05   198.1  848.94
#Mann= 3 , 0 , 0
       0      .1       0    87.1    .045       0 103.799      .1       0
Bank Sta=87.1,103.799
XS Rating Curve= 0 ,0
Exp/Cntr=0.3,0.1

Type RM Length L Ch R = 1 ,8741.4  ,231.3,231.3,231.3
XS GIS Cut Line= 2
     1831018.423      412205.116     1831157.312      412153.033
#Sta/Elev= 19
       0  876.79     9.3  870.71    18.5  863.94    27.8  855.02    37.1  844.83
    45.5  840.12    46.4  839.61    55.6  839.44    60.5  839.93    64.9  840.37
    74.2  841.54    83.4  842.66    92.7  843.52     102  844.06   111.2  844.85
   120.5  846.05   129.8  847.17   139.1  848.36   148.3  849.78
#Mann= 3 , 0 , 0
       0      .1       0    45.5    .045       0    60.5      .1       0
Bank Sta=45.5,60.5
XS Rating Curve= 0 ,0
Exp/Cntr=0.3,0.1

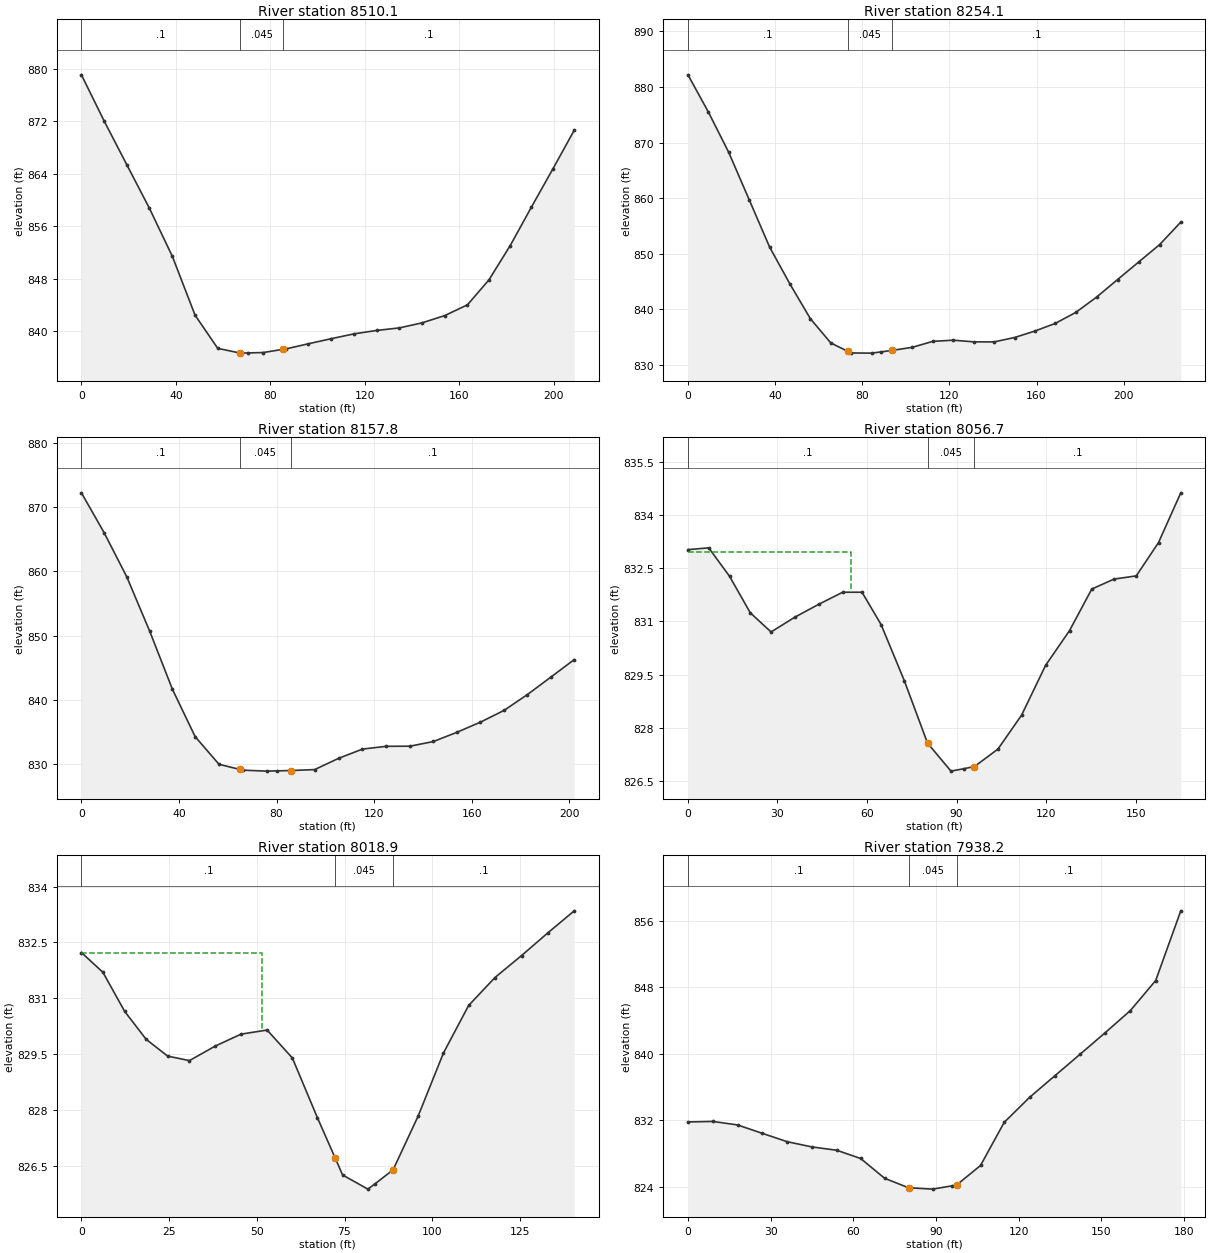
Type RM Length L Ch R = 1 ,8510.1  ,254,256,258
XS GIS Cut Line= 3
     1831095.463       412422.13     1831248.458      412364.622
     1831285.351       412338.58
#Sta/Elev= 25
       0  879.11     9.6  872.08    19.2   865.4    28.8  858.74    38.5  851.41
    48.1  842.45    57.7  837.39    67.3  836.66    70.4  836.69    76.9  836.75
    85.4  837.24    86.5   837.3    96.1  838.09   105.8  838.87   115.4   839.6
     125  840.12   134.6  840.51   144.2  841.28   153.8  842.39   163.4  844.03
   172.5  847.84   181.5  853.07   190.5  858.95   199.6  864.79   208.6  870.66
#Mann= 3 , 0 , 0
       0      .1       0    67.3    .045       0    85.4      .1       0
Bank Sta=67.3,85.4
XS Rating Curve= 0 ,0
Exp/Cntr=0.3,0.1

Type RM Length L Ch R = 1 ,8254.1  ,102,96.2,90.4
XS GIS Cut Line= 3
     1831162.738      412661.931     1831334.179      412614.188
     1831375.411      412589.231
#Sta/Elev= 27
       0  882.19     9.4  875.47    18.7  868.24    28.1  859.71    37.5  851.17
    46.8  844.54    56.2  838.28    65.6  833.91    73.4  832.41    74.9  832.12
    84.3  832.09    88.4   832.3    93.7  832.58     103  833.14   112.4  834.21
   121.8  834.42   131.1  834.12   140.5  834.11   149.9   834.9   159.2  836.06
   168.6  837.44     178  839.42   187.6  842.19   197.2  845.34   206.9   848.5
   216.5  851.63   226.2  855.67
#Mann= 3 , 0 , 0
       0      .1       0    73.4    .045       0    93.7      .1       0
Bank Sta=73.4,93.7
XS Rating Curve= 0 ,0
Exp/Cntr=0.3,0.1

Type RM Length L Ch R = 1 ,8157.8  ,136.2,101.1,66.7
XS GIS Cut Line= 4
     1831213.272      412761.658      1831255.46      412741.866
     1831323.168      412702.283     1831388.272      412661.137
#Sta/Elev= 24
       0   872.2     9.3     866    18.6  859.12      28  850.66    37.3  841.64
    46.6  834.28    56.4  829.97      65  829.17    66.2  829.06      76  828.91
      80  828.95    85.8     829    95.6  829.15   105.4   830.9   115.2  832.34
     125  832.77   134.7  832.79   144.3  833.52   153.9  834.95   163.5  836.52
   173.2  838.35   182.8  840.82   192.4  843.53     202  846.26
#Mann= 3 , 0 , 0
       0      .1       0      65    .045       0    85.8      .1       0
Bank Sta=65,85.8
XS Rating Curve= 0 ,0
Exp/Cntr=0.3,0.1

Type RM Length L Ch R = 1 ,8056.7  ,34.1,37.9,40.7
XS GIS Cut Line= 6
     1831348.168      412879.887     1831375.772      412860.096
     1831362.231      412834.054     1831361.189      412818.429
     1831334.627      412746.033     1831369.522      412716.866
#Sta/Elev= 24
       0  833.02   6.963  833.07  13.926  832.27  20.888  831.24  27.851   830.7
  35.879  831.12  43.825  831.48  51.852  831.82  58.324  831.82  64.713  830.91
  72.495  829.33  80.277  827.57  88.141  826.78  92.564  826.85  96.005  826.91
 103.868   827.4 111.814  828.36 119.842  829.76  127.87  830.74 135.324  831.91
 142.778  832.19 150.232  832.28 157.687  833.22 165.141  834.62
#Mann= 3 , 0 , 0
       0      .1       0  80.277    .045       0  96.005      .1       0
#XS Ineff= 2 , 0
          54.596  832.94
Permanent Ineff=
       F       F
Bank Sta=80.277,96.005
XS Rating Curve= 0 ,0
Skew Angle= 35
Exp/Cntr=0.3,0.1

Type RM Length L Ch R = 1 ,8018.9  ,48,80.6,113.5
XS GIS Cut Line= 5
     1831372.647      412898.116     1831401.814      412870.512
     1831390.356       412843.95     1831377.856      412769.991
     1831370.043       412731.45
#Sta/Elev= 23
       0  832.23   6.128   831.7  12.333  830.65  18.462   829.9   24.59  829.45
  30.795  829.33  38.149  829.72  45.503  830.04  52.934  830.15  60.134   829.4
  67.259   827.8  72.315  826.72   74.46  826.26   81.66  825.88  83.805  826.03
  88.861   826.4  95.985  827.84 103.186  829.53 110.387  830.81 117.894  831.56
 125.478  832.15 132.985  832.76 140.493  833.35
#Mann= 3 , 0 , 0
       0      .1       0  72.315    .045       0  88.861      .1       0
#XS Ineff= 2 , 0
           51.57  832.21
Permanent Ineff=
       F       F
Bank Sta=72.315,88.861
XS Rating Curve= 0 ,0
Skew Angle= 40
Exp/Cntr=0.3,0.1

Type RM Length L Ch R = 1 ,7938.2  ,85.6,86.2,86.8
XS GIS Cut Line= 4
     1831365.356      412910.616     1831411.189      412881.971
     1831465.356      412854.366     1831521.606      412823.637
#Sta/Elev= 23
       0  831.81       9  831.87      18  831.45      27  830.44      36  829.44
      45  828.81      54  828.41    62.7  827.42    71.4  825.04    80.1   823.9
    80.9  823.89    88.8  823.74    95.9  824.14    97.5  824.23   106.2  826.58
   114.8  831.76     124  834.76   133.2  837.36   142.3  839.93   151.5  842.54
   160.6  845.19   169.8   848.8   178.9  857.17
#Mann= 3 , 0 , 0
       0      .1       0    80.1    .045       0    97.5      .1       0
Bank Sta=80.1,97.5
XS Rating Curve= 0 ,0
Exp/Cntr=0.3,0.1

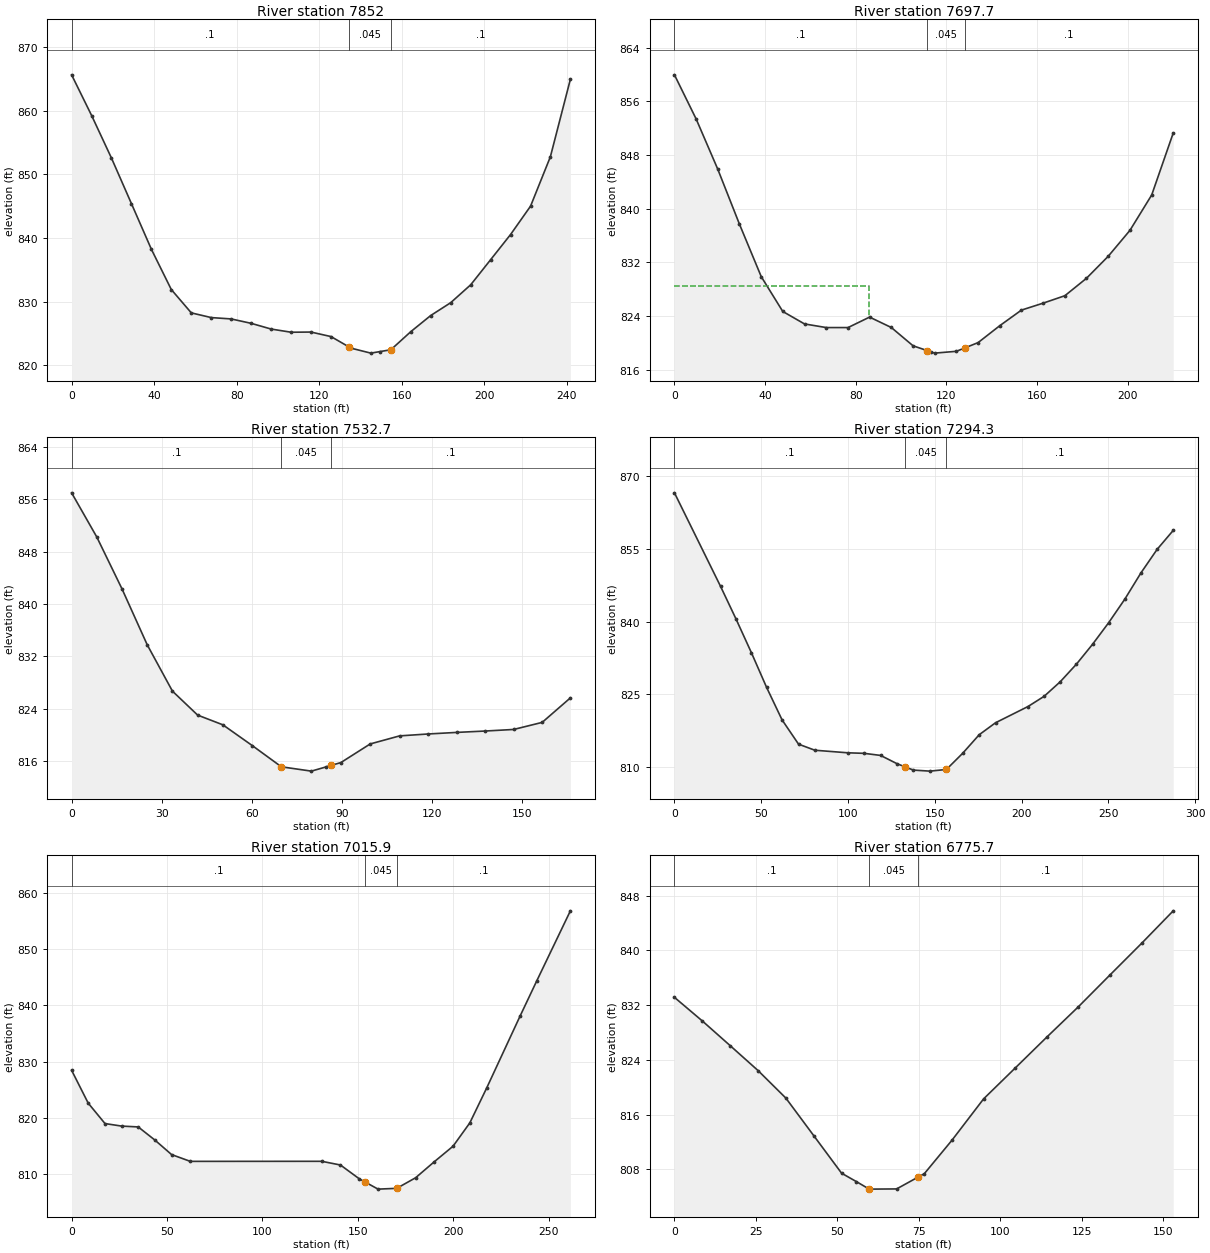
Type RM Length L Ch R = 1 ,7852    ,153.6,154.2,155
XS GIS Cut Line= 2
       1831347.2      413006.983     1831565.298      412902.816
#Sta/Elev= 28
       0  865.61     9.7  859.22    19.3  852.55      29  845.38    38.7  838.19
    48.3   831.9      58  828.23    67.7  827.49    77.3  827.28      87  826.59
    96.7  825.69   106.4  825.19     116  825.22   125.7  824.51   134.2  822.92
   135.4  822.69     145  821.91   149.2  822.14   154.7  822.44   164.4  825.29
     174  827.81   183.7  829.83   193.4  832.64     203  836.56   212.7  840.53
   222.4  844.99     232  852.74   241.7  864.92
#Mann= 3 , 0 , 0
       0      .1       0   134.2    .045       0   154.7      .1       0
Bank Sta=134.2,154.7
XS Rating Curve= 0 ,0
Exp/Cntr=0.3,0.1

Type RM Length L Ch R = 1 ,7697.7  ,164.5,165,165.2
XS GIS Cut Line= 2
      1831426.41      413135.021     1831628.233       413047.13
#Sta/Elev= 27
       0  859.97     9.6  853.37    19.1  845.92    28.7   837.7    38.3  829.89
    47.8   824.7    57.4  822.84      67   822.3    76.6   822.3    86.1  823.86
    95.7  822.31   105.3  819.58   111.6  818.86   113.1  818.69   114.8  818.49
   124.4  818.76   128.1  819.26     134  820.06   143.6  822.59   153.1   824.9
   162.7  825.94   172.3  827.05   181.8  829.64   191.4  832.92     201  836.79
   210.6  842.06   220.1   851.3
#Mann= 3 , 0 , 0
       0      .1       0   111.6    .045       0   128.1      .1       0
#XS Ineff= 2 , 0
           85.92  828.56
Permanent Ineff=
       F       F
Bank Sta=111.6,128.1
XS Rating Curve= 0 ,0
Exp/Cntr=0.3,0.1

Type RM Length L Ch R = 1 ,7532.7  ,244.1,238.4,232.6
XS GIS Cut Line= 4
     1831500.194       413273.91     1831547.937      413257.634
     1831602.191      413234.847     1831645.594      413197.955
#Sta/Elev= 21
       0  856.97     8.4  850.22    16.8   842.3    25.2  833.77    33.6   826.7
      42  823.04    50.4  821.56    60.2  818.39    69.9  815.15    79.9  814.49
    84.9  815.15   86.41  815.36    89.7  815.79    99.5  818.64   109.3  819.87
   118.8  820.16   128.3   820.4   137.8  820.61   147.3  820.85   156.8  821.93
   166.2  825.67
#Mann= 3 , 0 , 0
       0      .1       0    69.9    .045       0   86.41      .1       0
Bank Sta=69.9,86.41
XS Rating Curve= 0 ,0
Exp/Cntr=0.3,0.1

Type RM Length L Ch R = 1 ,7294.3  ,273.5,278.4,283.3
XS GIS Cut Line= 4
     1831604.361       413515.88     1831656.444      413482.243
     1831754.101      413407.373     1831808.354      413320.568
#Sta/Elev= 29
       0  866.49    26.6  847.22    35.4  840.59    44.3  833.63    53.1  826.46
      62  819.78    71.5  814.78    80.9  813.53    99.9     813   109.3  812.89
   118.8  812.46   128.3  810.75   132.6  810.15   137.7  809.44   147.2  809.23
   156.7  809.57   166.1  812.91   175.6  816.72     185  819.18   203.7  822.52
     213  824.62   222.3  827.62   231.6  831.23   240.9  835.32   250.2  839.77
   259.5  844.61   268.8  850.02   278.1  854.85   287.4  858.76
#Mann= 3 , 0 , 0
       0      .1       0   132.6    .045       0   156.7      .1       0
Bank Sta=132.6,156.7
XS Rating Curve= 0 ,0
Exp/Cntr=0.3,0.1

Type RM Length L Ch R = 1 ,7015.9  ,235.3,240.2,243.5
XS GIS Cut Line= 4
     1831735.654      413715.533     1831786.653      413703.597
     1831920.116      413640.663      1831978.71      413622.217
#Sta/Elev= 22
       0  828.44     8.7  822.58    17.5  818.94    26.2  818.49    34.9  818.34
    43.6  816.01    52.4  813.41    62.2   812.2   131.1  812.21   140.9  811.55
   150.8  809.08   153.8  808.52   160.6  807.25   170.4  807.39   180.3  809.28
   190.1  812.14   199.9   814.9   208.7  819.06   217.5  825.26     235  838.08
   243.8   844.4   261.4  856.87
#Mann= 3 , 0 , 0
       0      .1       0   153.8    .045       0   170.4      .1       0
Bank Sta=153.8,170.4
XS Rating Curve= 0 ,0
Exp/Cntr=0.3,0.1

Type RM Length L Ch R = 1 ,6775.7  ,239.5,230.2,222
XS GIS Cut Line= 4
     1831890.819      413911.931     1831927.712      413890.229
     1831968.944      413880.464     1832029.708      413850.082
#Sta/Elev= 21
       0  833.13     8.6  829.66    17.1  826.07    25.7  822.41    34.2   818.4
    42.8  812.88    51.3  807.42   55.84  806.19    59.8  805.09    59.9  805.09
    68.2  805.12    74.9  806.88    76.7  807.35    85.2  812.25    94.9  818.29
   104.6   822.8   114.3  827.32     124  831.76   133.7  836.41   143.4  841.03
   153.1  845.78
#Mann= 3 , 0 , 0
       0      .1       0    59.8    .045       0    74.9      .1       0
Bank Sta=59.8,74.9
XS Rating Curve= 0 ,0
Exp/Cntr=0.3,0.1

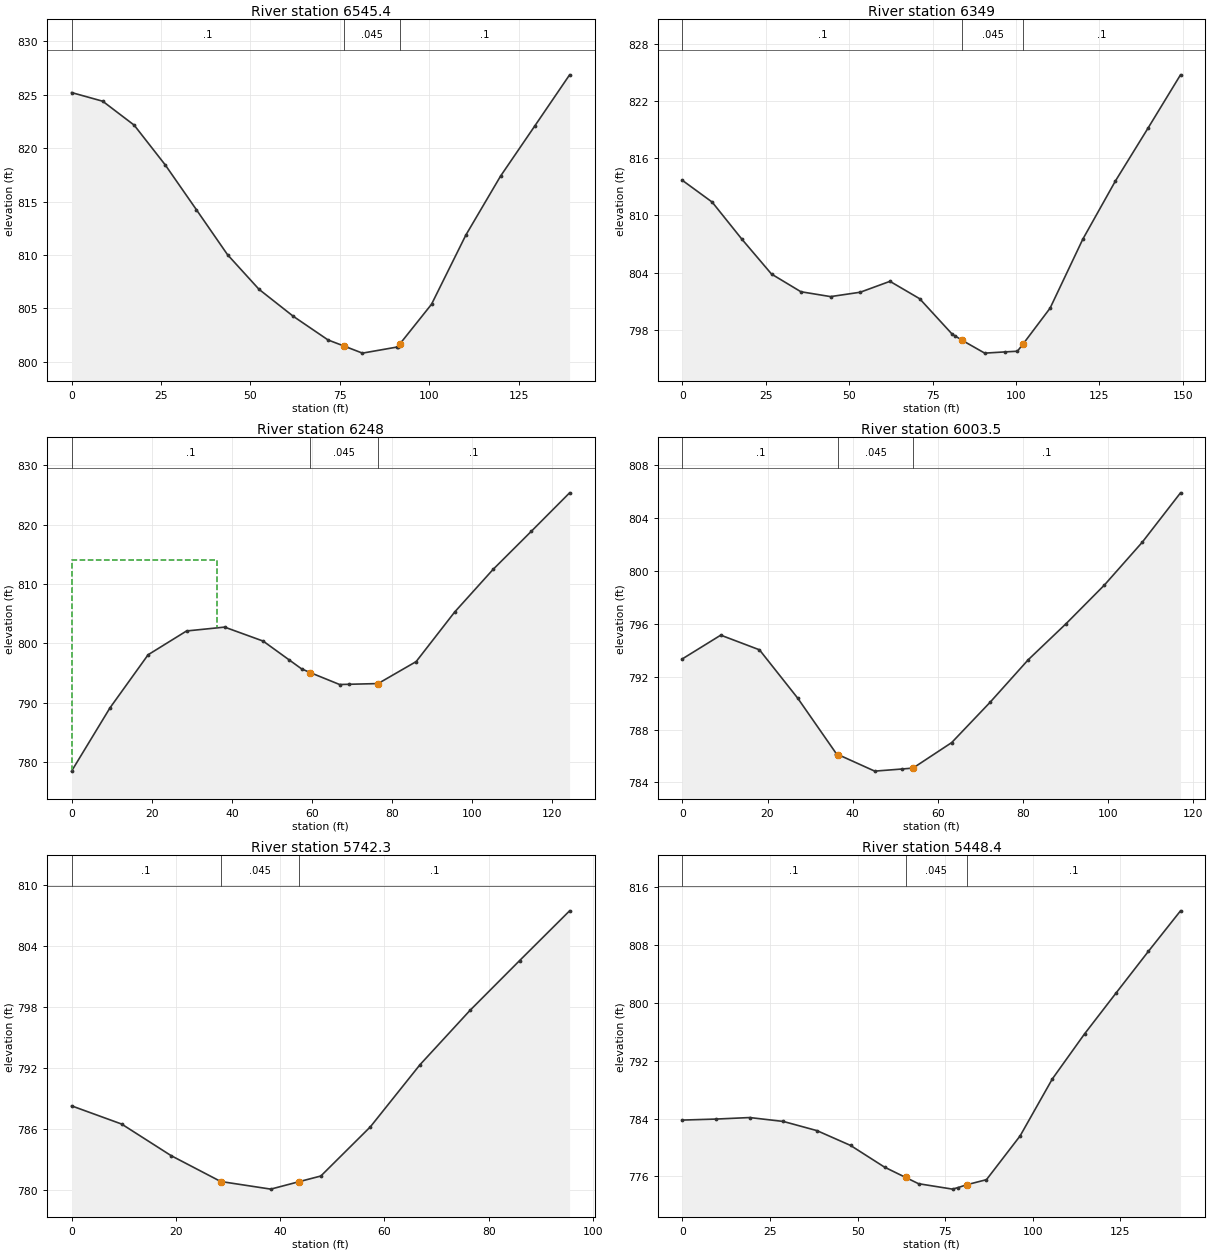
Type RM Length L Ch R = 1 ,6545.4  ,204.2,196.4,188.7
XS GIS Cut Line= 3
     1832011.262      414098.563      1832062.26      414086.627
     1832131.705      414034.543
#Sta/Elev= 19
       0  825.21     8.7   824.4    17.5  822.16    26.2  818.43    34.9  814.24
    43.6  810.03    52.4  806.79      62  804.26    71.7  802.05    76.1  801.49
    81.3  800.82      91  801.39    91.1  801.43   91.76  801.68   100.6  805.39
   110.2  811.87   119.9  817.39   129.5   822.1   139.2  826.87
#Mann= 3 , 0 , 0
       0      .1       0    76.1    .045       0   91.76      .1       0
Bank Sta=76.1,91.76
XS Rating Curve= 0 ,0
Exp/Cntr=0.3,0.1

Type RM Length L Ch R = 1 ,6349    ,100.7,101,101.1
XS GIS Cut Line= 3
     1832191.384      414267.833     1832228.276       414207.07
     1832271.679      414141.965
#Sta/Elev= 21
       0  813.67     8.9   811.4    17.8  807.52    26.7  803.86    35.5  802.01
    44.4   801.5    53.3  801.96    62.2   803.1    71.1  801.28    80.9  797.55
    81.8  797.37    83.9  796.91    90.6  795.58    96.8  795.71   100.4  795.78
  102.18  796.57   110.2  800.29     120  807.51   129.8  813.62   139.6  819.17
   149.3  824.73
#Mann= 3 , 0 , 0
       0      .1       0    83.9    .045       0  102.18      .1       0
Bank Sta=83.9,102.18
XS Rating Curve= 0 ,0
Exp/Cntr=0.3,0.1

Type RM Length L Ch R = 1 ,6248    ,246.7,244.5,242.3
XS GIS Cut Line= 2
      1832291.21      414293.875     1832360.654      414190.793
#Sta/Elev= 17
       0  778.49     9.6  789.16    19.1  798.09    28.7   802.1    38.2  802.75
    47.8   800.4    54.3  797.23    57.4  795.72   59.52   795.1    66.9  793.08
    69.3  793.12    76.5  793.24      86  796.94    95.6  805.28   105.2  812.47
   114.7  818.86   124.3  825.37
#Mann= 3 , 0 , 0
       0      .1       0   59.52    .045       0    76.5      .1       0
#XS Ineff= 2 , 0
           36.33  814.01
Permanent Ineff=
       F       F
Bank Sta=59.52,76.5
XS Rating Curve= 0 ,0
Exp/Cntr=0.3,0.1

Type RM Length L Ch R = 1 ,6003.5  ,272.1,261.1,250.2
XS GIS Cut Line= 3
     1832532.095      414370.915     1832565.733      414306.896
     1832576.583      414263.493
#Sta/Elev= 16
       0  793.36       9  795.15    18.1  794.04    27.1  790.38    36.2  786.17
    36.6  786.11    45.2  784.86    51.6  785.02    54.2  785.09    63.3  787.02
    72.3  790.06    81.3  793.29    90.2  796.02    99.2  798.94   108.1  802.18
   117.1  805.92
#Mann= 3 , 0 , 0
       0      .1       0    36.6    .045       0    54.2      .1       0
Bank Sta=36.6,54.2
XS Rating Curve= 0 ,0
Exp/Cntr=0.3,0.1

Type RM Length L Ch R = 1 ,5742.3  ,277.8,293.9,309.6
XS GIS Cut Line= 2
     1832809.873      414401.297     1832810.958      414305.811
#Sta/Elev= 12
       0  788.28     9.6  786.49    19.1  783.38    28.6  780.84    38.2  780.09
    43.6  780.82    47.8  781.38    57.3  786.22    66.8  792.32    76.4  797.67
    85.9  802.56    95.5  807.46
#Mann= 3 , 0 , 0
       0      .1       0    28.6    .045       0    43.6      .1       0
Bank Sta=28.6,43.6
XS Rating Curve= 0 ,0
Exp/Cntr=0.3,0.1

Type RM Length L Ch R = 1 ,5448.4  ,115.3,111.9,106.7
XS GIS Cut Line= 4
     1833057.269      414416.488     1833086.566       414378.51
     1833118.033      414341.618     1833135.394        414299.3
#Sta/Elev= 19
       0  783.79     9.6  783.93    19.2  784.14    28.8   783.6    38.4  782.33
      48  780.28    57.7  777.28    63.7  775.86    67.4  774.99    77.1  774.24
    78.7  774.46    81.2  774.85    86.8  775.55    96.4   781.6   105.6  789.48
   114.8  795.71   123.9  801.43     133  807.11   142.2  812.73
#Mann= 3 , 0 , 0
       0      .1       0    63.7    .045       0    81.2      .1       0
Bank Sta=63.7,81.2
XS Rating Curve= 0 ,0
Exp/Cntr=0.3,0.1

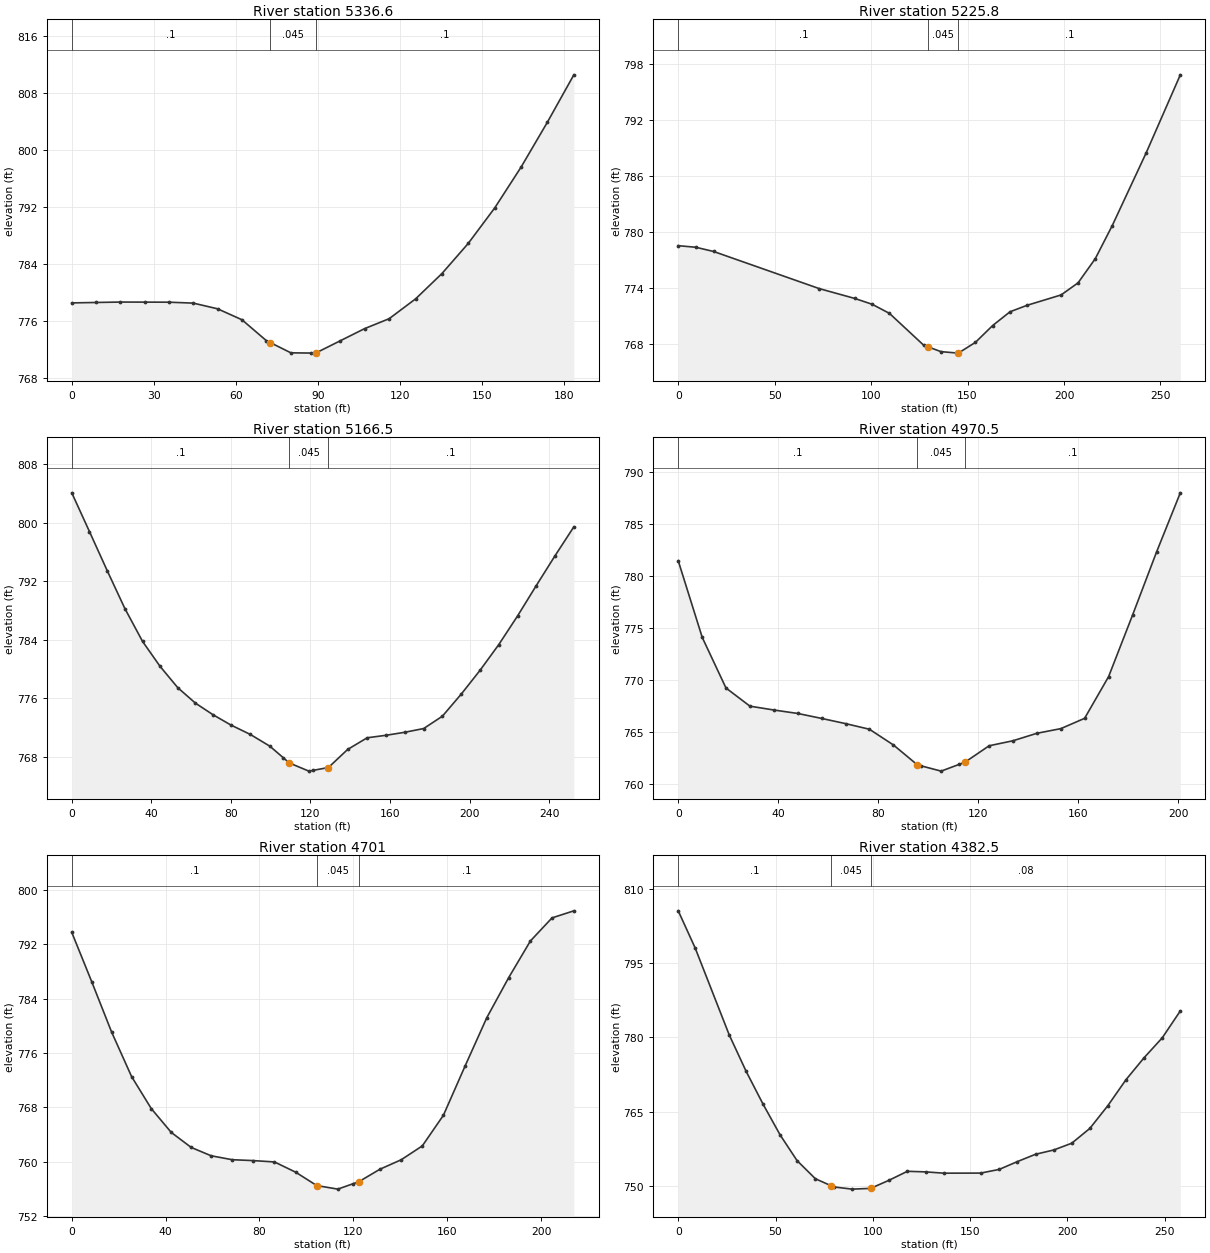
Type RM Length L Ch R = 1 ,5336.6  ,116.9,110.8,106.3
XS GIS Cut Line= 4
     1833154.925       414453.38     1833199.413      414409.978
      1833224.37      414362.234     1833211.349      414296.045
#Sta/Elev= 23
       0  778.54     8.9   778.6    17.8  778.66    26.6  778.65    35.5  778.64
    44.4  778.51    53.3  777.71    62.2  776.17    71.1  773.24    72.5  772.97
    80.1  771.52    87.5  771.49    89.1  771.48    98.1  773.21     107  774.92
     116  776.32   125.7  779.12   135.3  782.67   144.9   786.9   154.6   791.9
   164.2  797.62   173.8  803.92   183.5   810.6
#Mann= 3 , 0 , 0
       0      .1       0    72.5    .045       0    89.1      .1       0
Bank Sta=72.5,89.1
XS Rating Curve= 0 ,0
Exp/Cntr=0.3,0.1

Type RM Length L Ch R = 1 ,5225.8  ,70.2,59.3,48.5
XS GIS Cut Line= 4
     1833247.156      414536.931     1833304.665      414454.465
     1833327.451      414377.425     1833313.345        414299.3
#Sta/Elev= 21
       0  778.53     9.1  778.36    18.3  777.91    73.1  773.92    91.4  772.87
   100.5  772.24   109.5  771.26   127.3  767.83   129.7  767.65   136.2  767.15
   145.2  766.99   154.1  768.15     163  769.95     172  771.43   180.9  772.13
   198.5  773.24   207.3  774.54   216.2  777.13     225  780.68   242.6   788.5
   260.3  796.88
#Mann= 3 , 0 , 0
       0      .1       0   129.7    .045       0   145.2      .1       0
Bank Sta=129.7,145.2
XS Rating Curve= 0 ,0
Exp/Cntr=0.3,0.1

Type RM Length L Ch R = 1 ,5166.5  ,199.9,196,192
XS GIS Cut Line= 4
     1833408.831      414531.505      1833380.62      414456.635
     1833367.599      414389.361     1833354.578       414286.28
#Sta/Elev= 30
       0  804.05     8.9  798.76    17.8  793.44    26.7  788.26    35.6  783.77
    44.4  780.37    53.3  777.46    62.2  775.35    71.1  773.76      80  772.37
    89.8  771.08    99.6  769.48   106.4  767.89   109.4  767.19   119.2  766.08
   121.4  766.19     129  766.57   138.7  769.04   148.5  770.63     158  770.97
   167.4  771.38   176.9  771.89   186.3  773.57   195.8  776.59   205.2  779.82
   214.6  783.32   224.1  787.25   233.5  791.39     243  795.49   252.4  799.41
#Mann= 3 , 0 , 0
       0      .1       0   109.4    .045       0     129      .1       0
Bank Sta=109.4,129
XS Rating Curve= 0 ,0
Exp/Cntr=0.3,0.1

Type RM Length L Ch R = 1 ,4970.5  ,265.1,269.5,273.9
XS GIS Cut Line= 2
     1833591.123      414445.785     1833519.509      414258.068
#Sta/Elev= 24
       0   781.5     9.6  774.13    19.1  769.26    28.7  767.51    38.3  767.14
    47.8  766.81    57.4  766.33      67  765.83    76.5  765.29    86.1  763.78
    95.7  761.86    97.3  761.76   105.2  761.26   112.3   761.9   114.8  762.13
   124.4   763.7   133.9  764.18   143.5   764.9   153.1  765.35   162.6  766.34
   172.2  770.35   181.8  776.28   191.4  782.35   200.9  788.04
#Mann= 3 , 0 , 0
       0      .1       0    95.7    .045       0   114.8      .1       0
Bank Sta=95.7,114.8
XS Rating Curve= 0 ,0
Exp/Cntr=0.3,0.1

Type RM Length L Ch R = 1 ,4701    ,314.3,318.5,322.7
XS GIS Cut Line= 4
     1833813.562      414394.787     1833823.328      414336.193
     1833807.052      414238.537     1833812.477      414183.198
#Sta/Elev= 27
       0  793.76     8.5   786.5      17  779.07    25.5  772.53    33.9  767.81
    42.4  764.31    50.9   762.1    59.4  760.87    68.4  760.29    77.4  760.16
    86.4  759.96    95.4  758.46   104.4  756.49   104.7  756.47   113.4  755.96
   119.7  756.73   122.4  757.06   131.4   758.9   140.4  760.28   149.4  762.32
   158.4  766.83   167.7  774.13   176.9   781.2   186.2  787.08   195.5   792.5
   204.7  795.89     214  796.93
#Mann= 3 , 0 , 0
       0      .1       0   104.7    .045       0   122.4      .1       0
Bank Sta=104.7,122.4
XS Rating Curve= 0 ,0
Exp/Cntr=0.3,0.1

Type RM Length L Ch R = 1 ,4382.5  ,163.8,172,180.1
XS GIS Cut Line= 4
     1834109.569      414405.637      1834122.59      414345.958
     1834124.564      414232.636     1834116.752      414149.303
#Sta/Elev= 28
       0  805.57     8.7  798.07    26.2  780.53    34.9  773.17    43.6  766.54
    52.4  760.31    61.1  755.13    70.5  751.48    78.6  750.06      80  749.82
    89.4  749.38    98.9  749.53   108.3  751.16   117.8  752.98   127.2  752.86
   136.6   752.6   155.5  752.62     165  753.36   174.4  754.95   183.7  756.42
     193  757.28   202.3  758.65   211.6  761.64   220.9  766.26   230.2  771.49
   239.5  775.92   248.8  779.92   258.1  785.36
#Mann= 3 , 0 , 0
       0      .1       0    78.6    .045       0    98.9     .08       0
Bank Sta=78.6,98.9
XS Rating Curve= 0 ,0
Exp/Cntr=0.3,0.1

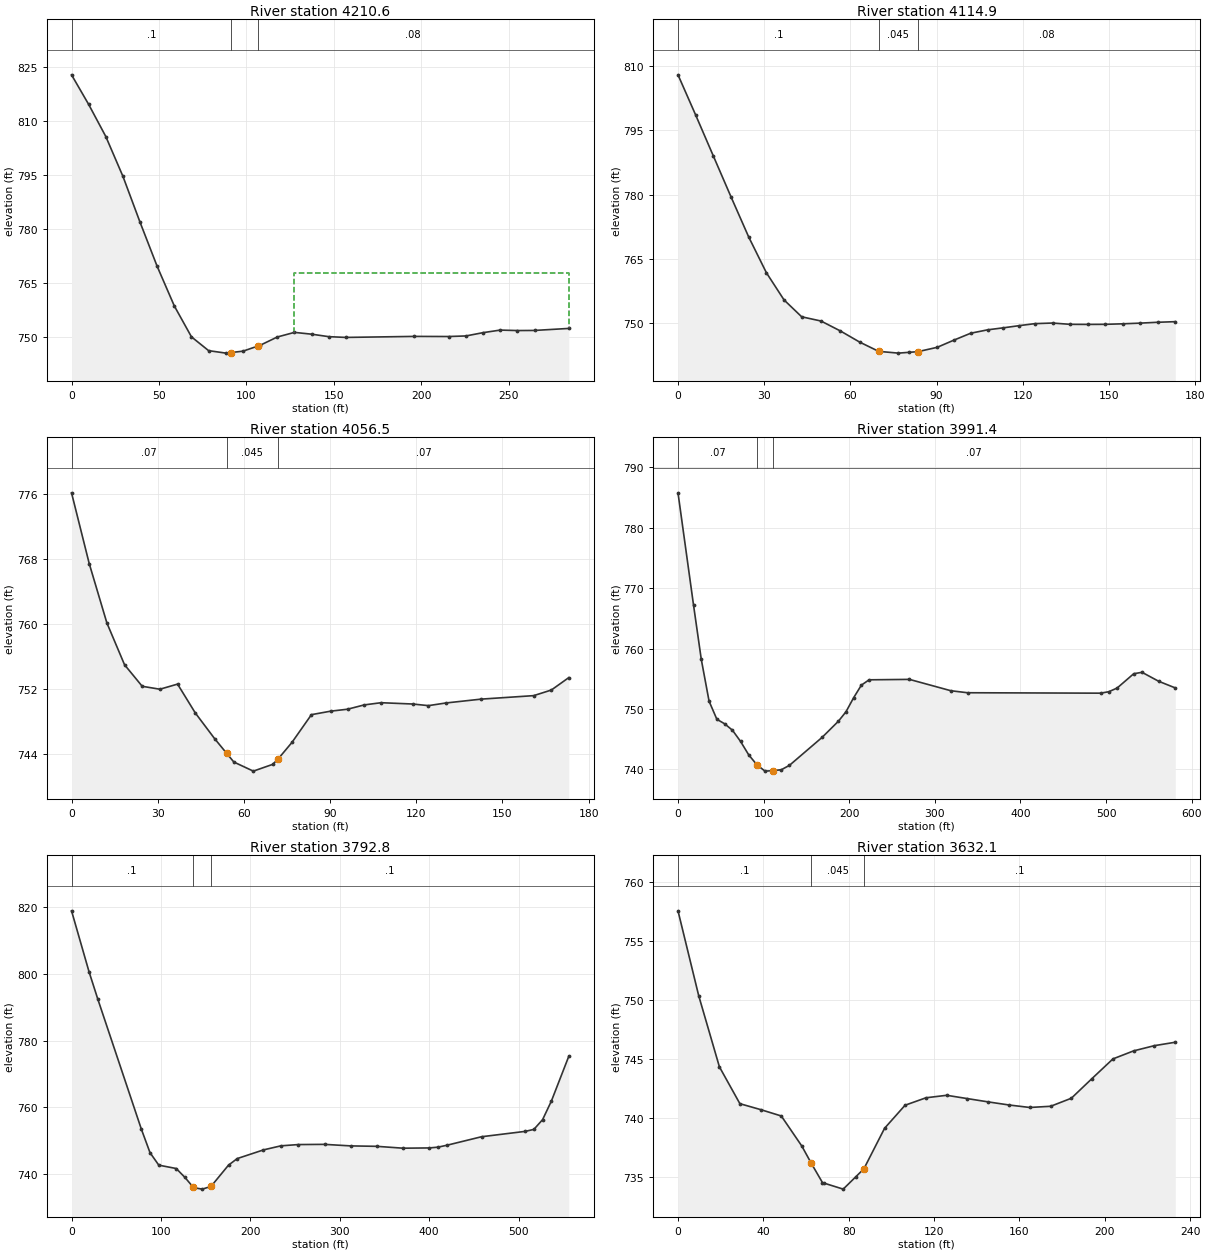
Type RM Length L Ch R = 1 ,4210.6  ,127,95.7,60.7
XS GIS Cut Line= 2
      1834241.08      414433.849     1834352.842      414172.347
#Sta/Elev= 27
       0  822.84     9.8  814.61    19.6  805.68    29.4   794.6    39.2  781.82
      49  769.54    58.8  758.54    68.6  749.95    78.4  746.12    88.3  745.43
    91.4   745.6    98.1  745.98   106.4  747.37   107.9  747.62   117.7  749.92
   127.5   751.2   137.3   750.7   147.1  750.01   156.9   749.8   196.1  750.08
   215.7  750.05   225.6  750.21   235.4  751.13   245.2  751.84     255  751.71
   264.8  751.74   284.4   752.3
#Mann= 3 , 0 , 0
       0      .1       0    91.4    .045       0   106.4     .08       0
#XS Ineff= 2 , 0
                          127.02          767.81
Permanent Ineff=
       F       F
Bank Sta=91.4,106.4
XS Rating Curve= 0 ,0
Exp/Cntr=0.3,0.1

Type RM Length L Ch R = 1 ,4114.9  ,50.3,58.4,61.6
XS GIS Cut Line= 6
     1834389.734      414456.635      1834401.67      414396.957
     1834353.927      414350.299     1834334.396      414335.108
     1834312.694      414326.427     1834347.417      414266.748
#Sta/Elev= 30
       0  807.85   6.152   798.5  12.304  788.97  18.455  779.46  24.607  770.13
  30.759  761.82  36.911  755.48  43.063  751.55   49.78  750.57  56.498  748.27
  63.286  745.65  69.862  743.51  76.721   743.1  80.469  743.29  83.509  743.44
  90.227  744.45  96.096  746.14 101.894  747.73 107.763  748.52 113.279  748.99
 118.723  749.49 124.239  749.96  130.39   750.1 136.472   749.8 142.553  749.78
 148.705   749.8 154.786  749.92 160.867  750.08 167.019  750.28   173.1  750.42
#Mann= 3 , 0 , 0
       0      .1       0  69.862    .045       0  83.509     .08       0
Bank Sta=69.862,83.509
XS Rating Curve= 0 ,0
Skew Angle= 45
Exp/Cntr=0.3,0.1

Type RM Length L Ch R = 1 ,4056.5  ,50.2,65.1,88.5
XS GIS Cut Line= 6
     1834432.052      414441.445     1834443.988      414381.766
     1834396.245      414335.108     1834376.713      414319.917
     1834355.012      414311.236     1834389.734      414251.557
#Sta/Elev= 27
       0  776.09   6.152  767.39  12.304  760.08  18.455  754.93  24.607  752.28
  30.759  751.92  36.911  752.55  43.063  749.01   49.78  745.85  54.023  744.02
  56.498  742.96  63.286  741.84  70.004  742.67   71.87  743.32  76.721  745.37
  83.509  748.79  90.227  749.22  96.096  749.46 101.894  749.99 107.763  750.26
 118.723   750.1 124.239   749.9  130.39  750.23 142.553   750.7 160.867  751.13
 167.019  751.82   173.1  753.35
#Mann= 3 , 0 , 0
       0     .07       0  54.023    .045       0   71.87     .07       0
Bank Sta=54.023,71.87
XS Rating Curve= 0 ,0
Skew Angle= 45
Exp/Cntr=0.3,0.1

Type RM Length L Ch R = 1 ,3991.4  ,183.4,198.7,213.9
XS GIS Cut Line= 5
     1834462.434      414463.146     1834491.731      414406.722
     1834491.731      414283.024      1834483.05      414229.856
      1834637.13      413927.122
#Sta/Elev= 30
       0  785.78    18.2  767.15    27.2  758.22    36.3   751.3    45.4  748.31
    54.5  747.56    63.6   746.5    73.1  744.64    82.6  742.42    92.1  740.79
   101.6  739.73   111.2  739.81   120.7  739.96   130.2  740.69   168.2   745.3
   187.3  747.98   196.2  749.55   205.2  751.89   214.2  753.96   223.2  754.84
   270.3  754.91   318.8  753.03   338.2   752.7   493.5  752.63   503.2  752.87
   512.9  753.48   532.3  755.85     542  756.08   561.4   754.6   580.8   753.5
#Mann= 3 , 0 , 0
       0     .07       0    92.1    .045       0   111.2     .07       0
Bank Sta=92.1,111.2
XS Rating Curve= 0 ,0
Exp/Cntr=0.3,0.1

Type RM Length L Ch R = 1 ,3792.8  ,160.3,160.7,161
XS GIS Cut Line= 2
     1834568.771      414594.439     1834913.823      414158.241
#Sta/Elev= 30
       0  818.98    19.5  800.76    29.3  792.54    78.1  753.43    87.8  746.36
    97.6  742.62   117.1  741.61   126.8  738.95   135.8  736.09   136.6  735.84
   146.4  735.42   156.1  736.26   175.6  742.63   185.4   744.6   214.7   747.2
   234.2  748.42   253.7   748.8     283  748.86   312.2   748.4   341.5  748.27
   370.8  747.71   400.1  747.79   409.8  748.02   419.6  748.58   458.6  751.15
   507.4  752.76   517.1  753.35   526.9  756.29   536.7  761.85   556.2  775.32
#Mann= 3 , 0 , 0
       0      .1       0   135.8    .045       0   156.1      .1       0
Bank Sta=135.8,156.1
XS Rating Curve= 0 ,0
Exp/Cntr=0.3,0.1

Type RM Length L Ch R = 1 ,3632.1  ,272.1,273.7,275.1
XS GIS Cut Line= 3
     1834729.361      414647.608     1834796.635      414565.142
     1834871.505      414463.146
#Sta/Elev= 28
       0  757.52     9.7  750.34    19.4  744.32      29   741.2    38.7   740.7
    48.4  740.16      58  737.62   62.44  736.16    67.7  734.52    68.4  734.48
    77.4  733.97    83.4  735.03    87.1  735.69    96.8  739.12   106.4  741.07
   116.2   741.7   125.9  741.91   135.6  741.63   145.4  741.35   155.1  741.09
   164.8  740.88   174.6  740.98   184.3  741.66     194  743.33   203.8  744.99
   213.5  745.67   223.2  746.11     233   746.4
#Mann= 3 , 0 , 0
       0      .1       0   62.44    .045       0    87.1      .1       0
Bank Sta=62.44,87.1
XS Rating Curve= 0 ,0
Exp/Cntr=0.3,0.1