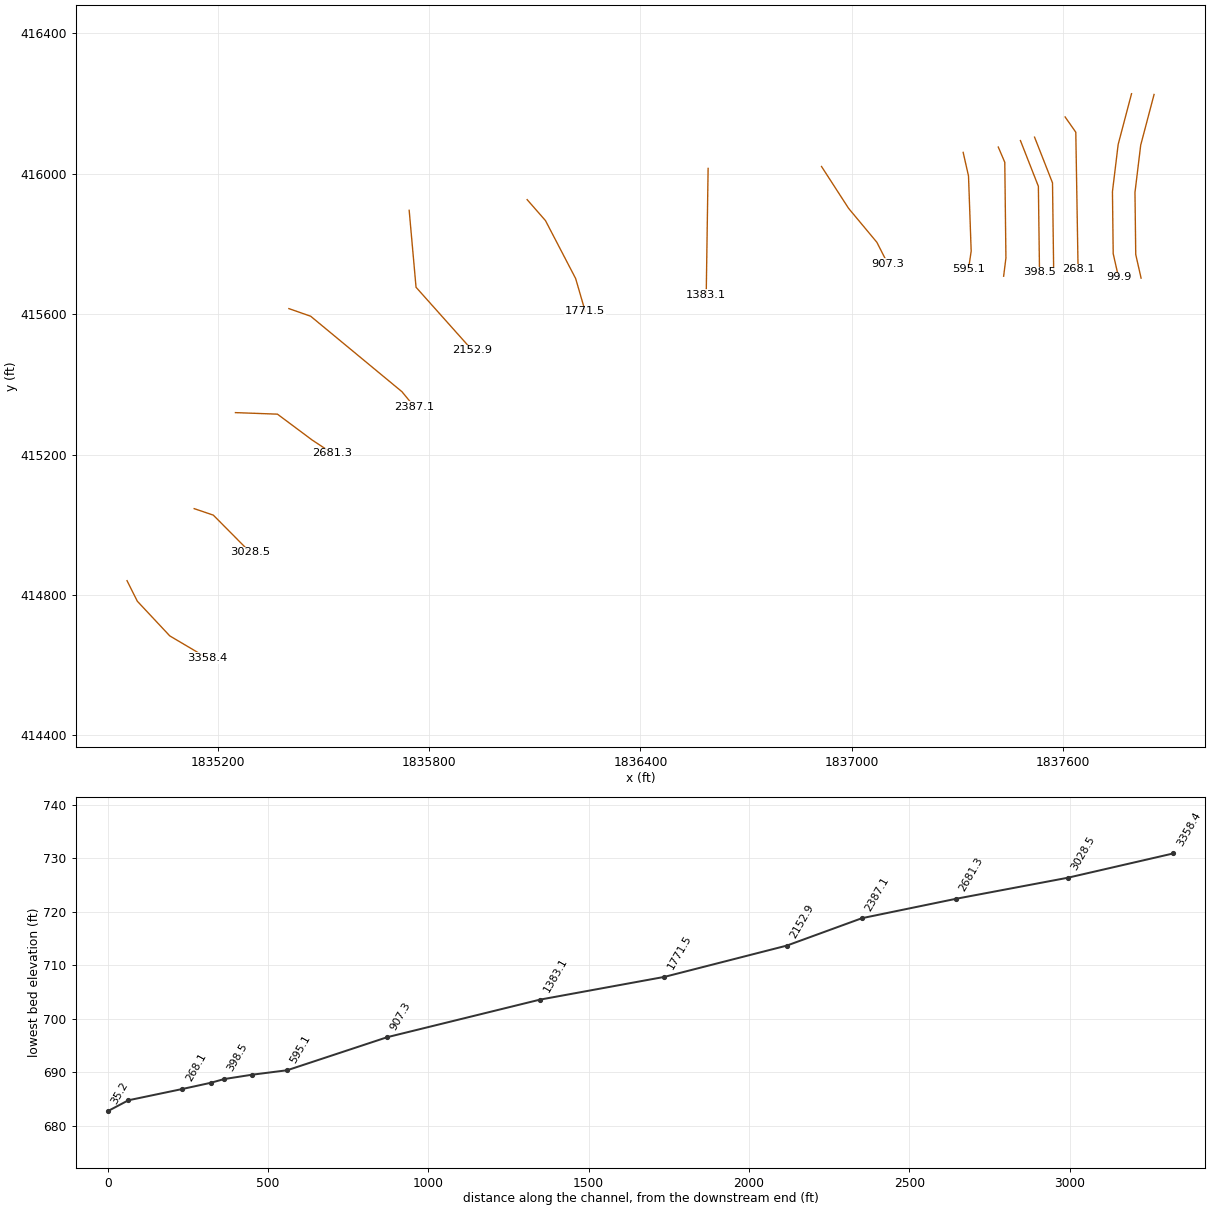
HEC-RAS study LNGBTTMCK.prj: LNGBTTMCK

--- LNGBTTMCK.g01 (geometry) --- (continued)

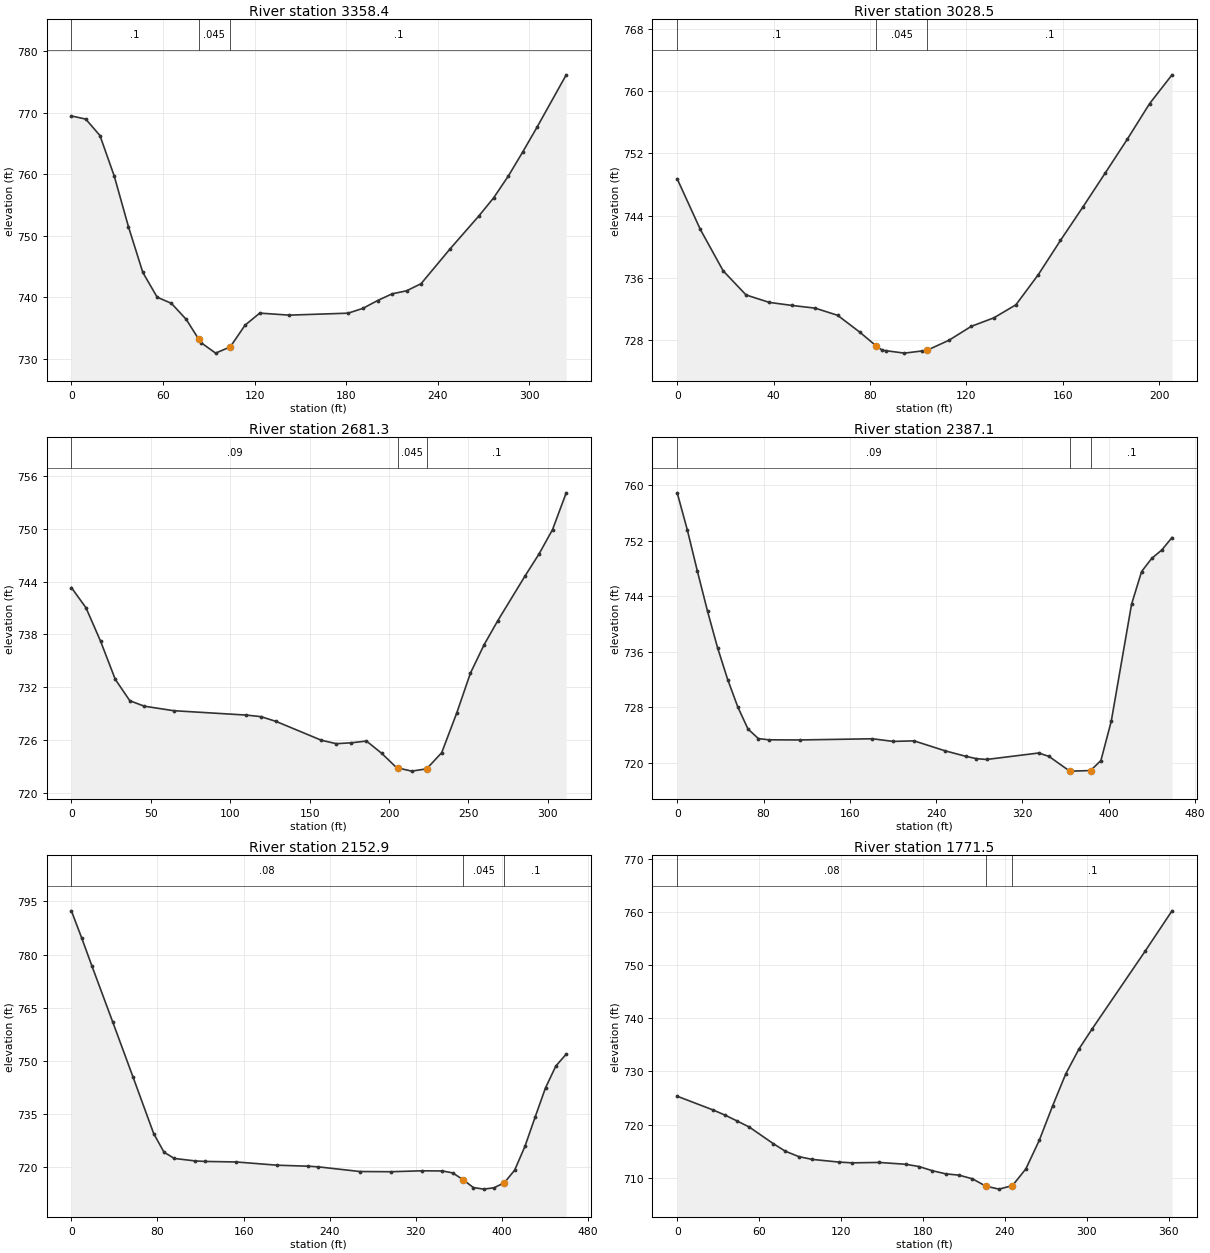
Type RM Length L Ch R = 1 ,3358.4  ,329.4,330,330.7
XS GIS Cut Line= 4
      1834940.95       414840.75     1834970.246      414782.156
     1835062.477      414683.415     1835168.814      414620.481
#Sta/Elev= 29
       0  769.46     9.4  768.95    18.7  766.28    28.1  759.67    37.4  751.45
    46.8  744.04    56.2  740.02    65.5  739.03    75.2  736.43    83.3  733.25
    84.8  732.66    94.5  730.94   104.1  731.96   113.8  735.49   123.4  737.44
   142.7  737.11   181.3  737.43     191  738.21   200.6  739.48   210.1  740.57
   219.6  741.06   229.1  742.22   248.2   747.9   267.2  753.29   276.7  756.18
   286.2  759.68   295.7  763.61   305.2  767.69   324.2  776.14
#Mann= 3 , 0 , 0
       0      .1       0    83.3    .045       0   104.1      .1       0
Bank Sta=83.3,104.1
XS Rating Curve= 0 ,0
Exp/Cntr=0.3,0.1

Type RM Length L Ch R = 1 ,3028.5  ,343.7,347.1,350.5
XS GIS Cut Line= 3
     1835131.922      415045.828     1835186.175      415027.382
     1835290.342       414922.13
#Sta/Elev= 26
       0  748.74     9.6  742.25    19.1  736.93    28.6  733.84    38.2  732.89
    47.8  732.49    57.3  732.15    66.6  731.23    75.8  729.07    82.6   727.3
    85.1  726.76    86.7  726.69    94.3  726.38   101.7  726.66   103.6  726.73
   112.8  728.03   122.1  729.82   131.4   730.9   140.6  732.58   149.9  736.45
   159.1  740.84   168.4  745.12   177.6  749.45   186.9  753.85   196.1  758.39
   205.4  762.08
#Mann= 3 , 0 , 0
       0      .1       0    82.6    .045       0   103.6      .1       0
Bank Sta=82.6,103.6
XS Rating Curve= 0 ,0
Exp/Cntr=0.3,0.1

Type RM Length L Ch R = 1 ,2681.3  ,294.9,294.2,293.3
XS GIS Cut Line= 4
     1835249.109      415319.266     1835368.467      415314.925
     1835467.208      415241.141     1835524.717      415203.163
#Sta/Elev= 28
       0  743.32     9.2  741.02    18.4  737.21    27.6   732.9    36.8  730.46
    45.9  729.84    64.3  729.33   110.2  728.83   119.4  728.65   128.9  728.11
   157.4  725.97   166.8  725.58   176.3  725.68   185.8  725.88   195.3   724.5
   204.8  722.85   205.6  722.82   214.3  722.46   223.7  722.72   233.2  724.56
   242.7  729.09   251.3  733.61   259.9  736.83   268.5  739.56   285.8  744.68
   294.4  747.12     303  749.92   311.6  754.09
#Mann= 3 , 0 , 0
       0     .09       0   205.6    .045       0   223.7      .1       0
Bank Sta=205.6,223.7
XS Rating Curve= 0 ,0
Exp/Cntr=0.3,0.1

Type RM Length L Ch R = 1 ,2387.1  ,237.9,234.3,230.2
XS GIS Cut Line= 4
     1835401.019       415615.49     1835462.868      415593.788
       1835722.2      415378.945     1835758.007      415335.542
#Sta/Elev= 30
       0   758.9     9.4  753.55    18.7  747.62    28.1  741.86    37.4   736.6
    46.8  732.01    56.2  728.05    65.6  724.89    75.2  723.51    84.8  723.33
   113.7  723.31     181  723.48   200.2   723.1   219.5  723.18   248.4  721.74
   267.6  720.95   277.2  720.62   286.8   720.5     335  721.43   344.6  720.94
   363.8  718.82   364.2  718.82   383.1   718.9   392.7  720.35   402.3  726.01
   421.1  742.85   430.4  747.56   439.8  749.46   449.2  750.68   458.6  752.46
#Mann= 3 , 0 , 0
       0     .09       0   364.2    .045       0   383.1      .1       0
Bank Sta=364.2,383.1
XS Rating Curve= 0 ,0
Exp/Cntr=0.3,0.1

Type RM Length L Ch R = 1 ,2152.9  ,386.8,381.4,376.1
XS GIS Cut Line= 3
     1835742.816      415895.438     1835762.347      415676.254
     1835921.852      415497.217
#Sta/Elev= 30
       0  792.36     9.6  784.65    19.1  776.74    38.3  761.02    57.4  745.26
    76.5  729.36    86.1  724.11    95.7  722.36   114.8  721.67   124.4  721.52
   153.1  721.37   191.4  720.45     220  720.17   229.6  719.98     268  718.67
   296.8  718.61   325.6  718.87   344.7  718.83   354.3  718.28   363.9  716.37
   373.5  714.14   383.1  713.69   392.7  714.07   402.3   715.5   411.9  719.06
   421.5  725.83   431.1  734.22   440.6  742.36   450.2  748.51   459.8  751.86
#Mann= 3 , 0 , 0
       0     .08       0   363.9    .045       0   402.3      .1       0
Bank Sta=363.9,402.3
XS Rating Curve= 0 ,0
Exp/Cntr=0.3,0.1

Type RM Length L Ch R = 1 ,1771.5  ,399.8,388.4,376.9
XS GIS Cut Line= 4
     1836078.102       415925.82     1836130.186      415866.141
     1836215.906       415701.21     1836243.033      415607.894
#Sta/Elev= 29
       0  725.34    26.4  722.74    35.2  721.76      44  720.66    52.8  719.53
    70.4   716.4    79.2  714.98      89  713.97    98.8  713.44   118.3  712.94
   128.1  712.79   147.7  712.87   167.3  712.52     177   712.1   186.8  711.31
   196.6  710.72   206.4  710.47   216.2  709.78     226   708.4   235.7  707.84
   245.5  708.51   255.3  711.66   265.1  717.03   274.8  723.47   284.5  729.55
   294.2  734.25     304  738.09   342.8  752.73   362.3  760.26
#Mann= 3 , 0 , 0
       0     .08       0     226    .045       0   245.5      .1       0
Bank Sta=226,245.5
XS Rating Curve= 0 ,0
Exp/Cntr=0.3,0.1

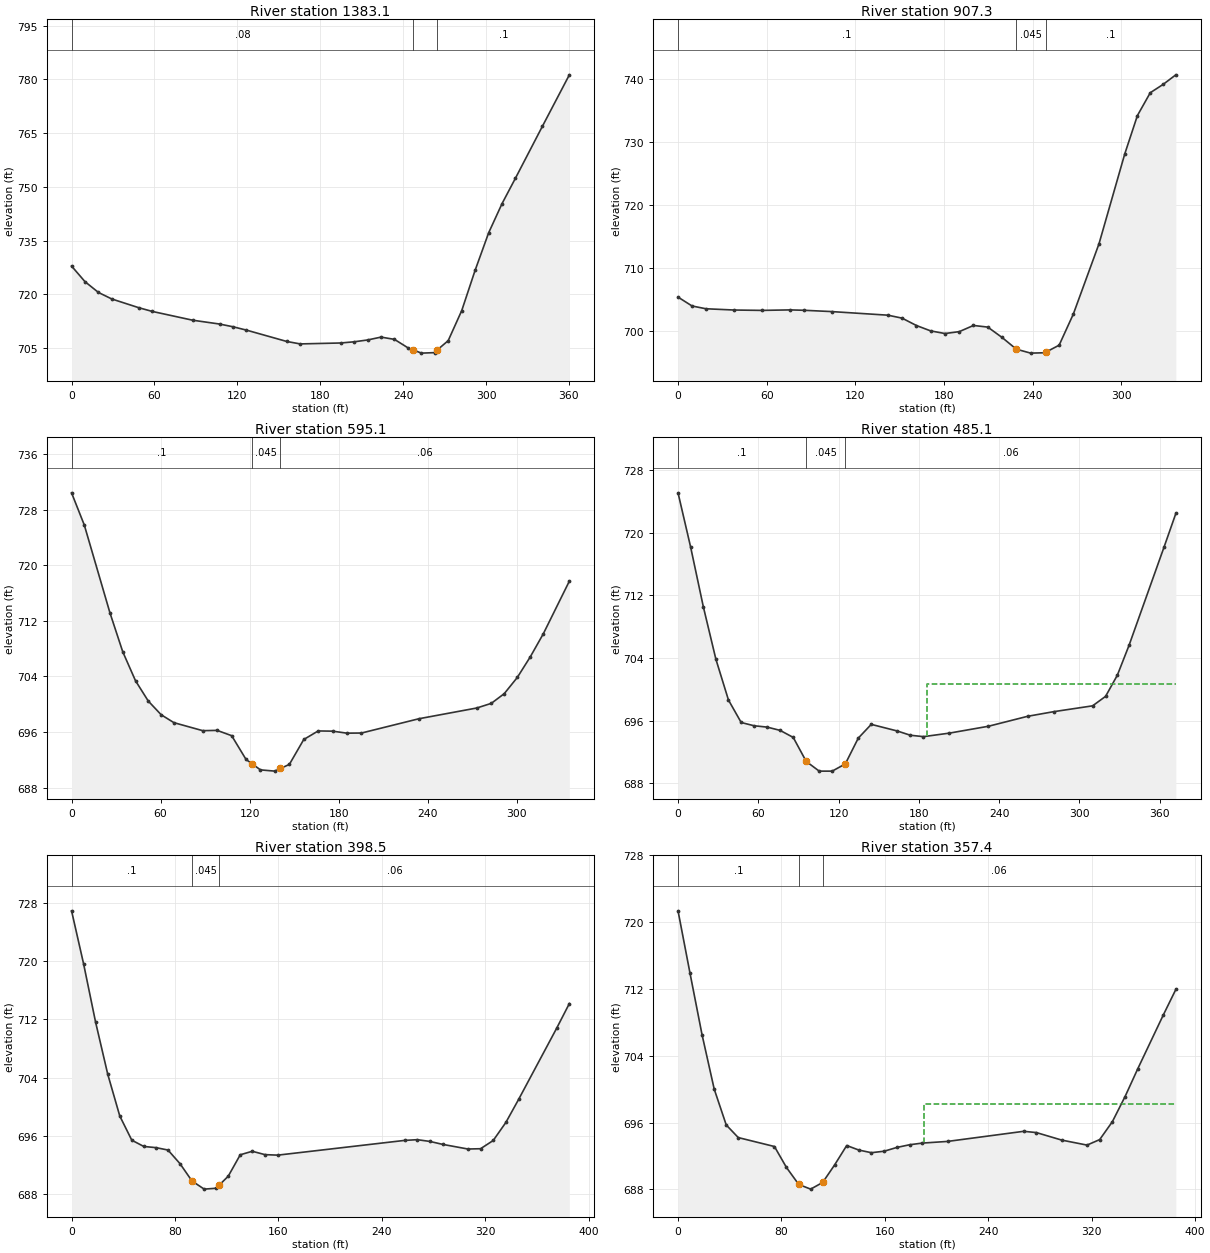
Type RM Length L Ch R = 1 ,1383.1  ,459.7,475.8,491.7
XS GIS Cut Line= 2
     1836592.425      416014.795        1836587.      415654.552
#Sta/Elev= 30
       0  727.88     9.7  723.53    19.5   720.5    29.2  718.68    48.7  716.25
    58.4  715.22    87.6  712.77   107.1   711.7   116.8  710.94   126.6     710
   155.8  706.83   165.5  706.15   194.8  706.41   204.5  706.74   214.2  707.25
     224  708.05   233.7  707.42   243.4  705.08   247.3  704.48   253.2  703.58
   262.9  703.72  264.66  704.46   272.6  707.06   282.4  715.45   292.1  726.71
   301.9  737.17   311.6  745.32   321.3  752.41   340.8  766.89   360.3  781.24
#Mann= 3 , 0 , 0
       0     .08       0   247.3    .045       0  264.66      .1       0
Bank Sta=247.3,264.66
XS Rating Curve= 0 ,0
Exp/Cntr=0.3,0.1

Type RM Length L Ch R = 1 ,907.3   ,327.5,312.2,297.2
XS GIS Cut Line= 4
     1836914.691      416020.221     1836991.731      415900.863
     1837072.026      415804.292     1837103.493      415742.443
#Sta/Elev= 29
       0  705.45     9.5  704.04    18.9   703.6    37.9   703.4    56.8  703.34
    75.8  703.42    85.2  703.36   104.2  703.15   142.1  702.58   151.7  702.11
   161.4  700.94     171  700.09   180.7  699.67   190.4  699.97     200  700.95
   209.7  700.69   219.4  699.04     229  697.19   238.7  696.56   248.3  696.62
   249.4  696.76     258  697.82   267.6  702.75     285  713.92   302.4  728.15
     311  734.26   319.7  737.88   328.4   739.2     337  740.72
#Mann= 3 , 0 , 0
       0      .1       0     229    .045       0   249.4      .1       0
Bank Sta=229,249.4
XS Rating Curve= 0 ,0
Exp/Cntr=0.3,0.1

Type RM Length L Ch R = 1 ,595.1   ,110.7,110,109.2
XS GIS Cut Line= 4
     1837317.252      416060.368     1837332.443      415993.094
     1837340.038      415779.335     1837332.443      415727.252
#Sta/Elev= 30
       0   730.4     8.6  725.76    25.9  713.12    34.5  707.54    43.1  703.37
    51.7  700.45    60.4  698.48      69  697.34    88.4  696.19    98.1  696.23
   107.9  695.47   117.6  692.05  121.83   691.4   127.3  690.55     137  690.37
   140.8  690.75   146.8  691.34   156.5  694.92   166.2  696.15   175.9  696.12
   185.6  695.83   195.4  695.85   234.2  697.91   273.1  699.45   282.9  700.12
   291.6  701.51   300.4  703.84   309.2  706.82     318  710.15   335.5   717.7
#Mann= 3 , 0 , 0
       0      .1       0  121.83    .045       0   140.8     .06       0
Bank Sta=121.83,140.8
XS Rating Curve= 0 ,0
Exp/Cntr=0.3,0.1

Type RM Length L Ch R = 1 ,485.1   ,78,86.6,95.3
XS GIS Cut Line= 4
     1837417.078      416075.559     1837435.524      416032.156
     1837438.779      415759.804     1837432.269      415707.721
#Sta/Elev= 29
       0  725.12     9.4   718.2    18.9  710.56    28.3  703.84    37.7  698.62
    47.2  695.75    56.9  695.33    66.6  695.16    76.3  694.74    86.1  693.84
    95.8  690.77   105.5  689.53   115.2  689.53     125  690.45   134.7  693.75
   144.4  695.51   163.9  694.66   173.6  694.12   183.4  693.94   202.8  694.39
     232  695.27   261.2  696.54   280.6  697.13   309.8  697.88   319.5  699.09
   328.3   701.8     337   705.6   363.3  718.23     372  722.48
#Mann= 3 , 0 , 0
       0      .1       0    95.8    .045       0     125     .06       0
#XS Ineff= 2 , 0
                          185.71          700.73
Permanent Ineff=
       F       F
Bank Sta=95.8,125
XS Rating Curve= 0 ,0
Exp/Cntr=0.3,0.1

Type RM Length L Ch R = 1 ,398.5   ,41,41.1,41
XS GIS Cut Line= 3
     1837480.012      416094.005      1837531.01      415963.797
     1837534.265      415718.571
#Sta/Elev= 30
       0  726.88     9.3  719.62    18.6  711.61      28  704.47    37.3  698.75
    46.6  695.43    55.9  694.57    65.3  694.41    74.6  694.08    83.9  692.21
    93.2  689.83   102.6  688.72   111.9  688.84  114.44  689.31   121.2  690.49
   130.5  693.43   139.8  693.91   149.6  693.45   159.5  693.38   257.6   695.4
   267.4   695.5   277.2  695.26     287  694.86   306.6  694.22   316.4  694.26
   326.2  695.39     336  697.87   345.8  701.01   375.3  710.79   385.1  714.17
#Mann= 3 , 0 , 0
       0      .1       0    93.2    .045       0  114.44     .06       0
Bank Sta=93.2,114.44
XS Rating Curve= 0 ,0
Exp/Cntr=0.3,0.1

Type RM Length L Ch R = 1 ,357.4   ,100.3,89.3,79.2
XS GIS Cut Line= 3
      1837520.16      416103.771     1837571.158      415973.563
     1837574.413      415728.337
#Sta/Elev= 30
       0  721.34     9.3  713.85    18.6   706.5      28     700    37.3  695.71
    46.6   694.2    74.6  693.13    83.9  690.62    93.4  688.59   102.6  688.03
   111.9  688.83   121.2  690.94   130.5  693.25   139.8  692.71   149.6  692.39
   159.5  692.57   169.3  693.02   179.1  693.34   188.9  693.54   208.5  693.74
   267.4  694.95   277.2   694.8   296.8   693.9   316.4   693.3   326.2  693.96
     336   696.1   345.8   699.1   355.7  702.45   375.3  708.84   385.1  711.93
#Mann= 3 , 0 , 0
       0      .1       0    93.4    .045       0   111.9     .06       0
#XS Ineff= 2 , 0
                          190.48          698.26
Permanent Ineff=
       F       F
Bank Sta=93.4,111.9
XS Rating Curve= 0 ,0
Exp/Cntr=0.3,0.1

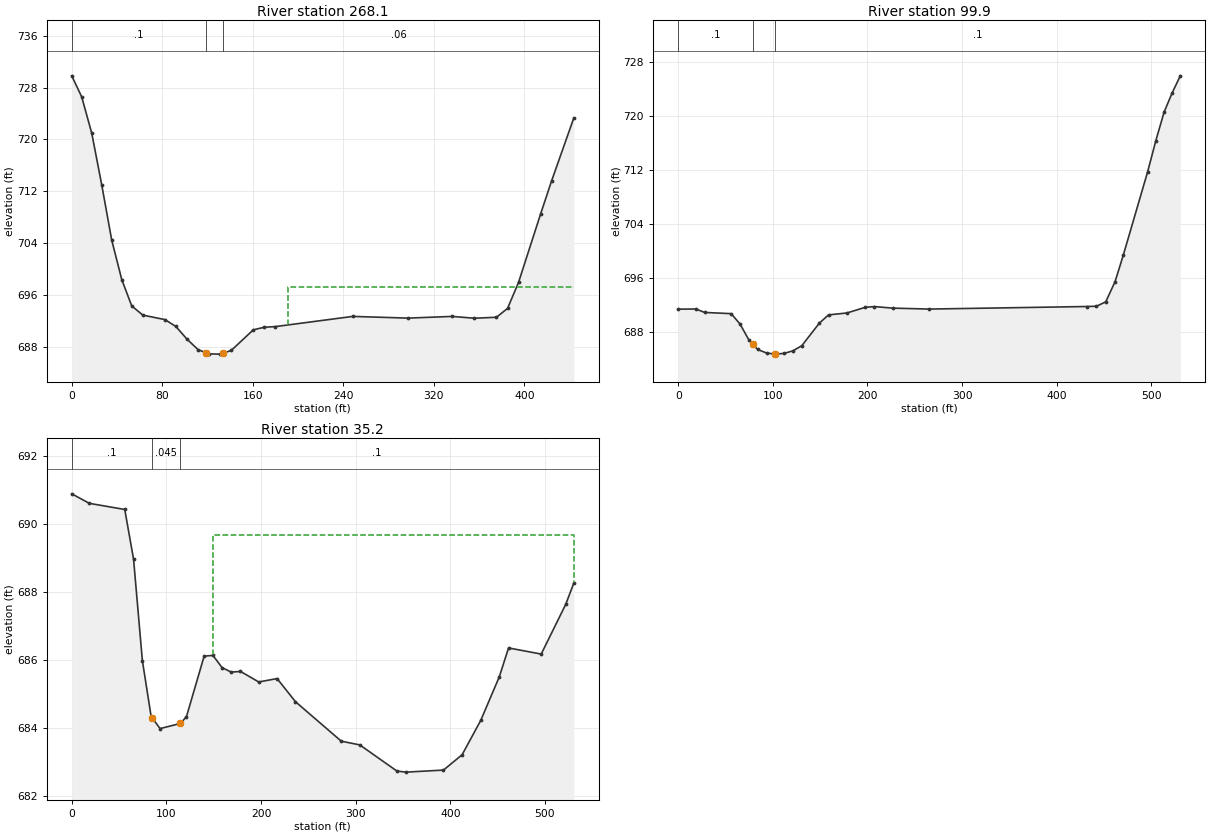
Type RM Length L Ch R = 1 ,268.1   ,174,168.2,161.4
XS GIS Cut Line= 3
     1837606.965       416161.28     1837637.347      416117.877
     1837643.858      415727.252
#Sta/Elev= 30
       0  729.81     8.8  726.55    17.7  720.92    26.5  712.96    35.3  704.45
    44.2  698.35      53   694.3    62.8  692.88    82.3  692.19      92  691.13
   101.8  689.18   111.6  687.55   118.5  687.09   121.4   686.9   131.1  686.86
   133.5     687   140.9  687.42   160.4  690.61   170.2  691.01     180  691.11
   248.3  692.68   297.2  692.42   336.2  692.68   355.8   692.4   375.3  692.55
   385.1  693.91   394.8  697.92   414.4  708.53   424.1  713.63   443.7  723.32
#Mann= 3 , 0 , 0
       0      .1       0   118.5    .045       0   133.5     .06       0
#XS Ineff= 2 , 0
                          190.93          697.27
Permanent Ineff=
       F       F
Bank Sta=118.5,133.5
XS Rating Curve= 0 ,0
Exp/Cntr=0.3,0.1

Type RM Length L Ch R = 1 ,99.9    ,62.5,64.7,66.9
XS GIS Cut Line= 5
     1837795.767      416227.469      1837757.79      416083.155
     1837741.514      415948.606     1837743.684       415771.74
     1837758.875      415704.465
#Sta/Elev= 30
       0  691.42    18.6  691.44      28  690.93      56  690.75    65.3  689.21
    74.6  686.87    79.1  686.18    83.9  685.44    93.3  684.92   102.6  684.75
   111.9  684.86   121.2  685.24   130.6     686   149.2  689.36   158.9  690.57
   178.3  690.85   197.6  691.69   207.3   691.8   226.7  691.57   265.4  691.43
   432.2  691.81     442  691.85   451.8   692.5   461.6  695.48   470.3   699.4
   496.1   711.8   504.7  716.38   513.4   720.6     522  723.49   530.6  726.01
#Mann= 3 , 0 , 0
       0      .1       0    79.1    .045       0   102.6      .1       0
Bank Sta=79.1,102.6
XS Rating Curve= 0 ,0
Exp/Cntr=0.3,0.1

Type RM Length L Ch R = 1 ,35.2    ,41.3,35.2,29
XS GIS Cut Line= 5
     1837859.786      416225.299     1837821.809      416080.984
     1837805.533      415946.436     1837807.703       415769.57
     1837822.894      415702.295
#Sta/Elev= 30
       0  690.88    18.6   690.6      56  690.42    65.3  688.96    74.6  685.98
    83.9  684.33    85.1  684.29    93.3  683.98  114.79  684.13   121.2  684.33
   139.9  686.11   149.2  686.13   158.9  685.77   168.6  685.64   178.3  685.66
   197.6  685.35     217  685.45   236.4  684.77   284.8  683.61   304.4   683.5
   343.7  682.73   353.5   682.7   392.8  682.76   412.5  683.21   432.2  684.22
   451.8   685.5   461.6  686.35   496.1  686.17     522  687.63   530.6  688.26
#Mann= 3 , 0 , 0
       0      .1       0    85.1    .045       0  114.79      .1       0
#XS Ineff= 2 , 0
                           148.8          689.68
Permanent Ineff=
       F       F
Bank Sta=85.1,114.79
XS Rating Curve= 0 ,0
Exp/Cntr=0.3,0.1

Chan Stop Cuts=-1
Use User Specified Reach Order=0
Composite Channel Slope=5